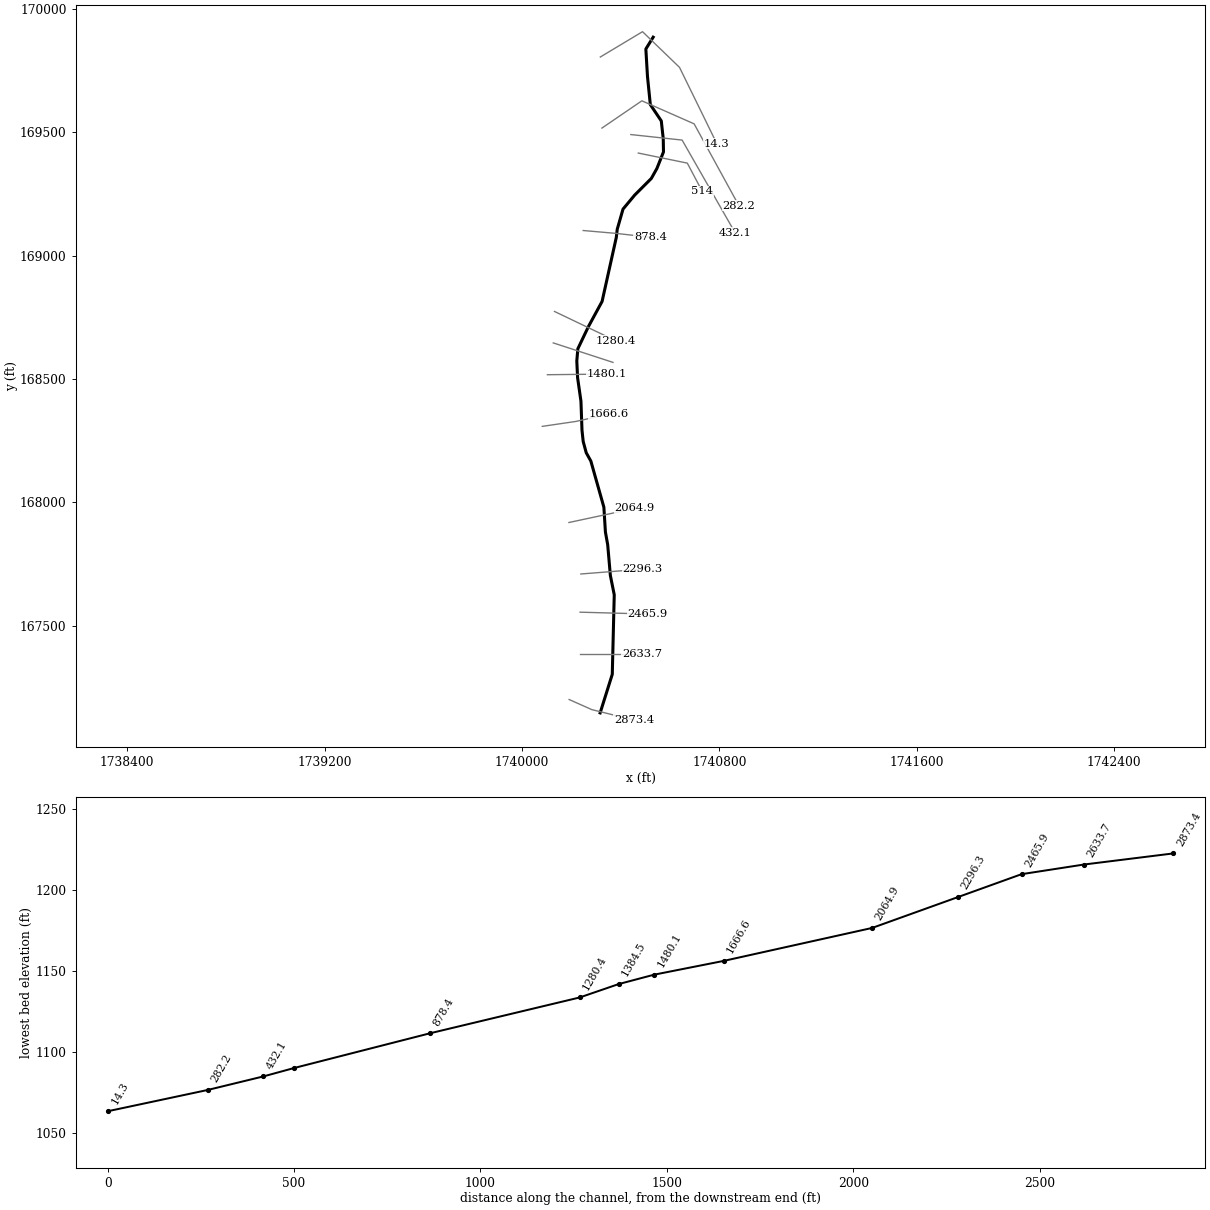
--- Harman Branch Trib 1.prj (project) ---

Proj Title=Harman Branch Trib 1
Current Plan=p01
Default Exp/Contr=0,0
English Units
Geom File=g01
Flow File=f01
Plan File=p01
BEGIN DESCRIPTION:
END DESCRIPTION:
DSS Export Rating Curves= 0
DSS Export Rating Curve Sorted= 0
DSS Export Volume Flow Curves= 0
DXF OffsetX= 0
DXF OffsetY= 0
DXF ScaleX= 0
DXF ScaleY= 0

--- Harman Branch Trib 1.p01 (plan) ---

Plan Title=Floodplain
Program Version=4.00
Geom File=g01
Flow File=f01
K Sum by GR=0
Std Step Tol=0.01
Critical Tol=0.01
Num of Std Step Trials=20
Max Error Tol=0.3
Flow Tol Ratio=0.001
Split Flow NTrial=30
Split Flow Tol=0.02
Split Flow Ratio=0.02
Log Output Level=0
Friction Slope Method=1
Unsteady Friction Slope Method=2
Unsteady Bridges Friction Slope Method=1
Global Log Level=0
CheckData=False
Run HTab=0
Run UNet=0
Run PostProcess=0
UNET Theta=0
UNET Theta Warmup=0
UNET ZTol=0
UNET ZSATol=0
UNET MxIter=0
UNET MaxInSteps=0
UNET DtIC=0
UNET DtMin=0
UNET MaxCRTS=0
UNET WFStab=0
UNET SFStab=0
UNET WFX=0
UNET SFX=0
UNET DSS MLevel=0
UNET DZMax Abort=0
UNET Convert EG Bridges=0
UNET Use Existing IB Tables=0
UNET Froude Limit=0
UNET Froude Power=0
Write IC File=0
Echo Input=False
Echo Output=False
Write Detailed=0

--- Harman Branch Trib 1.f01 (steady flow) ---

Flow Title=NFF Regression Equation
Program Version=4.00
Number of Profiles=1
Profile Names=P100yr
River Rch & RM=Harman Branch...,Main      ,2873.4
613.0238
River Rch & RM=Harman Branch...,Main      ,2633.7
615.5660
River Rch & RM=Harman Branch...,Main      ,282.2
682.4804
Boundary for River Rch & Prof#=Harman Branch...,Main      ,1
Up Type=0
Dn Type=3
Dn Slope=0.052416

--- Harman Branch Trib 1.g01 (geometry) ---

Geom Title=Geometry
Program Version=4.00

River Reach=Harman Branch...,Main
Reach XY= 30
     1740316.681      167146.546     1740365.845      167302.985
     1740373.833      167625.249     1740358.112      167703.533
     1740347.271      167828.216     1740338.036      167879.843
     1740331.821       167980.36     1740279.003      168167.374
     1740260.365      168200.812     1740248.032      168246.407
     1740243.115      168291.948     1740238.906      168409.808
     1740225.226       168505.57     1740222.069      168572.918
     1740226.278      168622.377     1740269.423      168712.877
     1740324.542      168814.256     1740382.171      169073.769
     1740385.902      169106.602     1740409.382      169188.527
     1740456.806      169245.437     1740524.014      169312.645
     1740546.747      169353.168     1740573.432      169420.377
     1740572.444      169473.748     1740564.537      169545.899
     1740520.061      169612.119     1740508.549      169726.003
     1740501.931      169837.418     1740531.617      169885.372

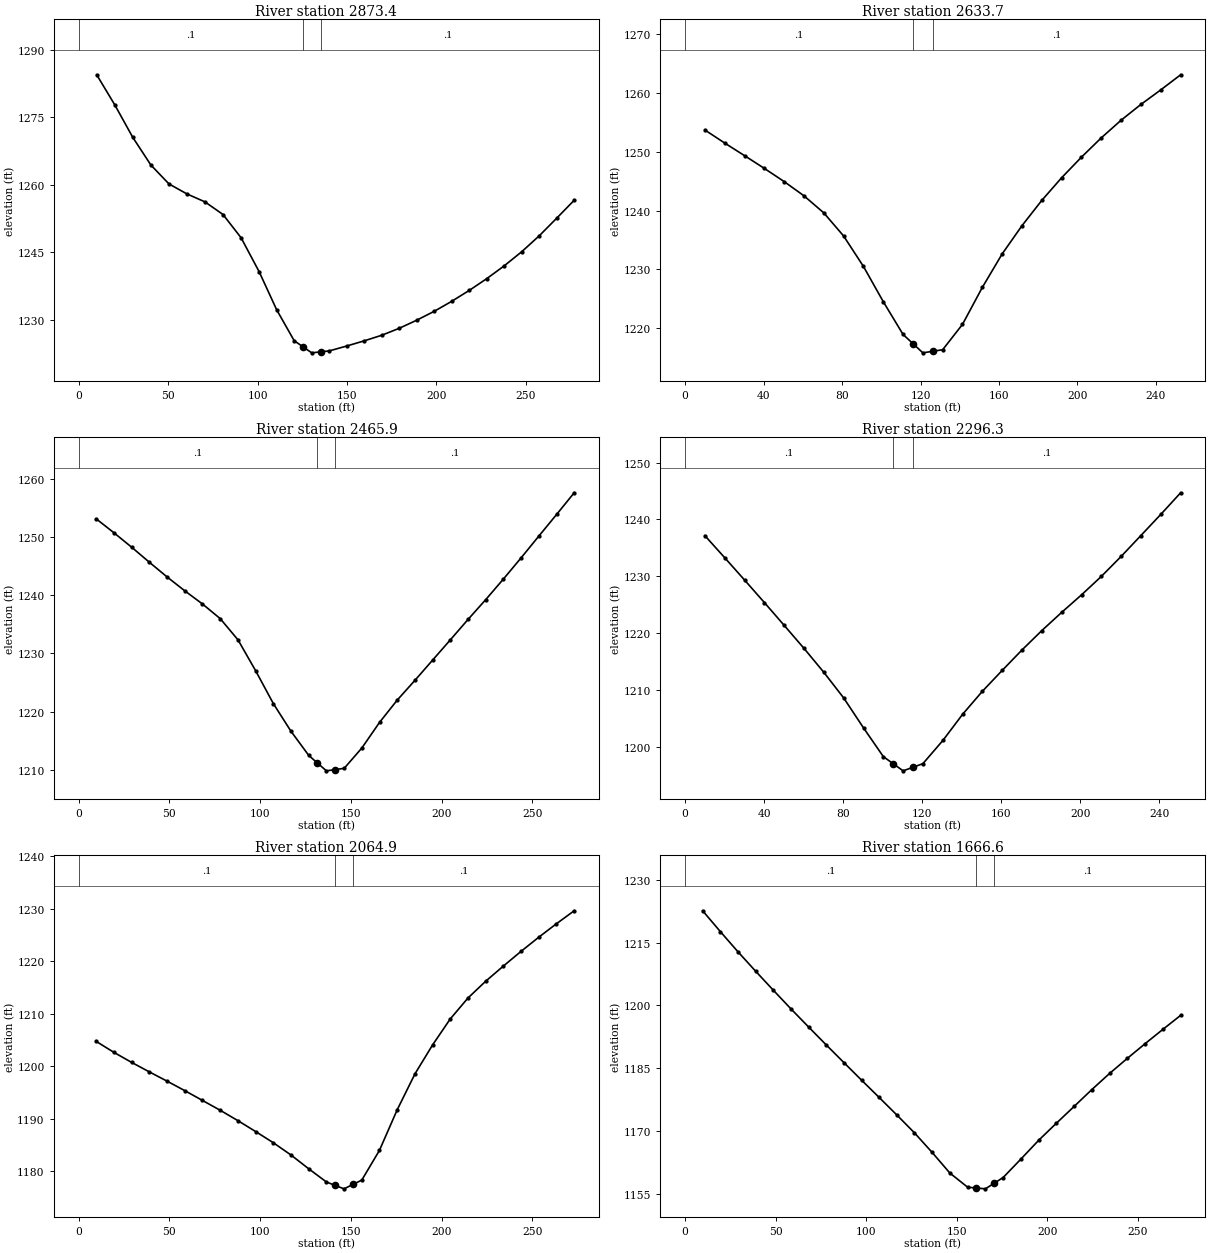
Type RM Length L Ch R = 1 ,2873.4  ,234.9,239.8,244.6
XS GIS Cut Line= 3
     1740191.029      167200.804     1740283.235      167159.782
     1740454.237      167117.689
#Sta/Elev= 30
    10.1 1284.41    20.2 1277.73    30.3 1270.49    40.4 1264.36    50.5 1260.17
    60.6 1257.94    70.6 1256.19    80.7 1253.38    90.8 1248.22   100.9 1240.68
   110.7 1232.22   120.5 1225.35   125.3 1224.03   130.3 1222.66   135.3 1222.88
   140.1 1223.09   149.8 1224.17   159.6 1225.32   169.4 1226.56   179.2 1228.11
     189 1229.91   198.8 1231.89   208.5 1234.09   218.3 1236.51   228.1 1239.13
   237.9 1241.98   247.7 1245.12   257.5 1248.66   267.2 1252.55     277 1256.54
#Mann= 3 , 0 , 0
       0      .1       0   125.3    .045       0   135.3      .1       0
Bank Sta=125.3,135.3
XS Rating Curve= 0 ,0
Exp/Cntr=0.3,0.1

Type RM Length L Ch R = 1 ,2633.7  ,168.3,167.7,167.2
XS GIS Cut Line= 2
      1740233.25        167383.4     1740485.807        167383.4
#Sta/Elev= 27
    10.1 1253.69    20.2 1251.47    30.3 1249.33    40.4 1247.16    50.5 1244.92
    60.6  1242.5    70.7  1239.6    80.8 1235.67    90.9  1230.5     101 1224.51
   111.1 1218.93   116.2 1217.35   121.2  1215.8   126.2 1216.06   131.3 1216.33
   141.4 1220.64   151.5 1226.92   161.6 1232.61   171.7 1237.41   181.8 1241.71
   191.9 1245.56     202 1249.06   212.1 1252.34   222.3 1255.37   232.4 1258.05
   242.5 1260.52   252.6 1263.08
#Mann= 3 , 0 , 0
       0      .1       0   116.2    .045       0   126.2      .1       0
Bank Sta=116.2,126.2
XS Rating Curve= 0 ,0
Exp/Cntr=0.3,0.1

Type RM Length L Ch R = 1 ,2465.9  ,167.5,169.6,171.7
XS GIS Cut Line= 3
     1740235.353      167554.833     1740371.802      167551.094
      1740508.25      167547.356
#Sta/Elev= 30
     9.7  1253.1    19.5  1250.7    29.3 1248.21      39 1245.64    48.8 1243.11
    58.5 1240.74    68.2 1238.49      78 1235.97    87.8 1232.32    97.5 1227.03
   107.3 1221.36     117 1216.62   126.8 1212.47   131.5 1211.19   136.5 1209.83
   141.5 1210.05   146.3 1210.26     156 1213.74   165.8 1218.16   175.5 1221.97
   185.3 1225.38     195 1228.84   204.8 1232.33   214.5 1235.82   224.3 1239.24
     234 1242.76   243.8 1246.42   253.5 1250.13   263.3 1253.85     273 1257.58
#Mann= 3 , 0 , 0
       0      .1       0   131.5    .045       0   141.5      .1       0
Bank Sta=131.5,141.5
XS Rating Curve= 0 ,0
Exp/Cntr=0.3,0.1

Type RM Length L Ch R = 1 ,2296.3  ,228.8,231.4,234.1
XS GIS Cut Line= 2
     1740238.511       167709.62     1740488.438      167729.351
#Sta/Elev= 27
      10 1237.15    20.1 1233.24    30.1 1229.33    40.1 1225.38    50.1 1221.37
    60.2 1217.29    70.2 1213.09    80.2  1208.6    90.3  1203.3   100.3 1198.26
   105.3 1197.01   110.3 1195.76   115.3 1196.39   120.3 1197.02   130.4  1201.1
   140.4 1205.71   150.4 1209.76   160.5 1213.46   170.5 1217.05   180.5 1220.45
   190.5 1223.64   200.6 1226.74   210.6 1229.98   220.6 1233.49   230.6 1237.17
   240.7  1240.9   250.7 1244.69
#Mann= 3 , 0 , 0
       0      .1       0   105.3    .045       0   115.3      .1       0
Bank Sta=105.3,115.3
XS Rating Curve= 0 ,0
Exp/Cntr=0.3,0.1

Type RM Length L Ch R = 1 ,2064.9  ,398.1,398.3,398.4
XS GIS Cut Line= 3
     1740190.222      167918.299     1740323.702      167946.851
     1740457.183      167975.403
#Sta/Elev= 30
     9.7 1204.71    19.5 1202.61    29.2 1200.71      39 1198.89    48.8 1197.12
    58.5 1195.32    68.2 1193.46      78 1191.58    87.7 1189.61    97.5 1187.53
   107.3 1185.38     117 1183.05   126.7 1180.44   136.5 1177.91   141.2 1177.27
   146.2  1176.6   151.2 1177.45     156 1178.27   165.7 1183.92   175.5 1191.67
   185.3 1198.53     195 1204.04   204.7 1208.98   214.5 1212.99   224.2 1216.17
     234 1219.08   243.8  1221.9   253.5 1224.58   263.2 1227.14     273 1229.62
#Mann= 3 , 0 , 0
       0      .1       0   141.2    .045       0   151.2      .1       0
Bank Sta=141.2,151.2
XS Rating Curve= 0 ,0
Exp/Cntr=0.3,0.1

Type RM Length L Ch R = 1 ,1666.6  ,190.7,186.5,182.4
XS GIS Cut Line= 3
      1740082.23      168307.953     1740217.155      168327.741
     1740351.222      168357.103
#Sta/Elev= 30
     9.7 1222.59    19.5  1217.6    29.2  1212.8      39 1208.14    48.7 1203.64
    58.4  1199.2    68.2 1194.85    77.9 1190.59    87.7 1186.35    97.4 1182.18
   107.1 1178.06   116.9 1173.86   126.6 1169.61   136.4 1164.92   146.2 1159.99
     156 1156.62   160.8 1156.43   165.8 1156.23   170.8 1157.61   175.6 1158.93
   185.4 1163.33   195.2 1167.81     205 1171.89   214.8  1175.9   224.6 1179.93
   234.4 1183.78   244.2 1187.38     254 1190.88   263.8 1194.29   273.6 1197.63
#Mann= 3 , 0 , 0
       0      .1       0   160.8    .045       0   170.8      .1       0
Bank Sta=160.8,170.8
XS Rating Curve= 0 ,0
Exp/Cntr=0.3,0.1

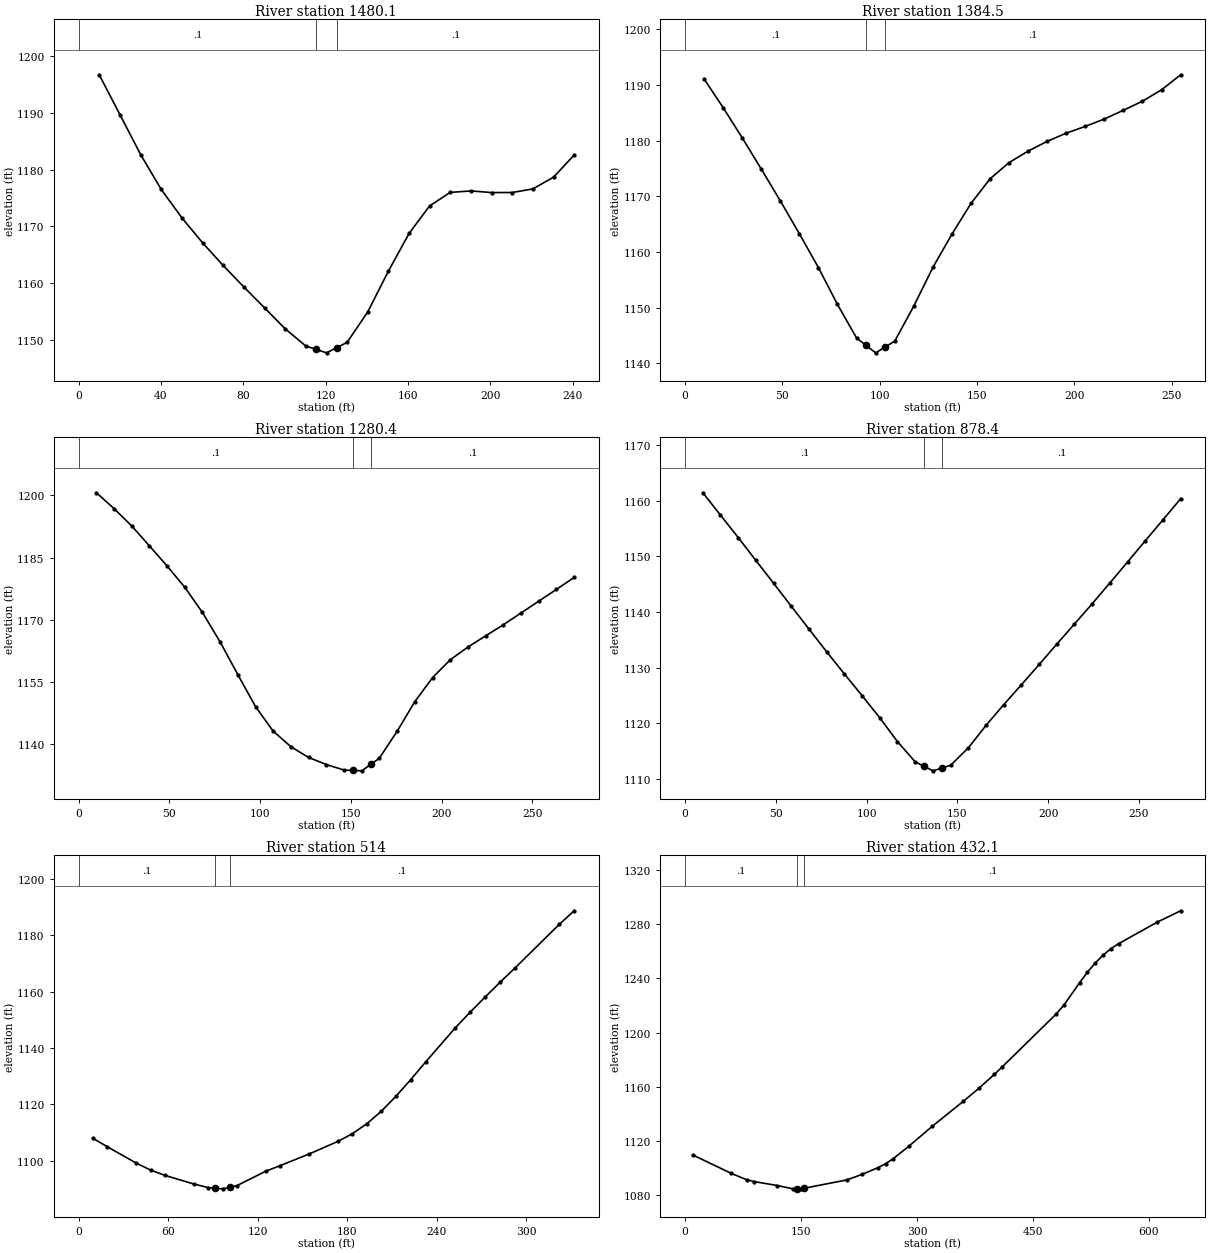
Type RM Length L Ch R = 1 ,1480.1  ,102.2,95.6,88.9
XS GIS Cut Line= 2
     1740103.025      168517.277     1740343.743      168519.908
#Sta/Elev= 26
      10 1196.69    20.1 1189.65    30.1 1182.65    40.1 1176.51    50.2 1171.48
    60.2 1167.11    70.2 1163.11    80.2 1159.35    90.3 1155.65   100.3 1151.98
   110.3 1148.94   115.4 1148.33   120.4 1147.73   125.4 1148.65   130.4 1149.57
   140.4 1154.92   150.5 1162.14   160.5 1168.75   170.5 1173.61   180.5 1175.98
   190.6 1176.24   200.6 1175.95   210.6 1175.96   220.7  1176.6   230.7 1178.67
   240.7 1182.56
#Mann= 3 , 0 , 0
       0      .1       0   115.4    .045       0   125.4      .1       0
Bank Sta=115.4,125.4
XS Rating Curve= 0 ,0
Exp/Cntr=0.3,0.1

Type RM Length L Ch R = 1 ,1384.5  ,106.7,104.1,101.5
XS GIS Cut Line= 2
     1740126.702      168646.186     1740368.736      168567.262
#Sta/Elev= 28
     9.8 1191.09    19.6 1185.93    29.4  1180.5    39.2 1174.89      49 1169.15
    58.7  1163.3    68.5 1157.21    78.3 1150.58    88.1 1144.56    92.9 1143.25
    97.9 1141.89   102.9 1142.96   107.7 1143.99   117.5 1150.29   127.3 1157.23
   137.1 1163.23   146.9 1168.75   156.7 1173.17   166.5 1176.09   176.2 1178.14
     186 1179.89   195.8 1181.37   205.6 1182.58   215.4 1183.91   225.2 1185.49
     235 1187.11   244.8 1189.16   254.6 1191.86
#Mann= 3 , 0 , 0
       0      .1       0    92.9    .045       0   102.9      .1       0
Bank Sta=92.9,102.9
XS Rating Curve= 0 ,0
Exp/Cntr=0.3,0.1

Type RM Length L Ch R = 1 ,1280.4  ,394.9,402.1,408.8
XS GIS Cut Line= 3
     1740131.611      168773.703     1740254.739      168714.783
     1740377.867      168655.862
#Sta/Elev= 30
     9.8  1200.6    19.5  1196.8    29.3 1192.59      39 1187.81    48.7 1182.99
    58.5 1177.84    68.2 1171.78      78 1164.65    87.8 1156.74    97.5 1149.08
   107.2  1143.2     117 1139.44   126.7 1136.87   136.5 1135.16   146.2 1133.84
     151 1133.75     156 1133.65     161 1135.22   165.7  1136.7   175.5  1143.2
   185.2  1150.3     195  1156.1   204.7 1160.38   214.5 1163.47   224.2 1166.14
     234 1168.83   243.7 1171.65   253.5  1174.5   263.2 1177.33     273 1180.21
#Mann= 3 , 0 , 0
       0      .1       0     151    .045       0     161      .1       0
Bank Sta=151,161
XS Rating Curve= 0 ,0
Exp/Cntr=0.3,0.1

Type RM Length L Ch R = 1 ,878.4   ,366.7,364.4,362.6
XS GIS Cut Line= 3
     1740247.963      169101.752     1740383.998      169089.847
     1740519.616      169074.436
#Sta/Elev= 30
     9.8  1161.4    19.5 1157.39    29.3 1153.35      39 1149.25    48.8 1145.14
    58.5 1141.03    68.3 1136.92      78 1132.85    87.8 1128.87    97.5 1124.99
   107.3 1120.99     117 1116.73   126.8 1113.09   131.6 1112.31   136.6 1111.49
   141.6    1112   146.3 1112.49   156.1 1115.64   165.8 1119.66   175.6 1123.39
   185.3 1126.95   195.1 1130.59   204.8 1134.25   214.5 1137.84   224.3 1141.49
     234 1145.21   243.8 1148.99   253.5 1152.77   263.3 1156.56     273 1160.34
#Mann= 3 , 0 , 0
       0      .1       0   131.6    .045       0   141.6      .1       0
Bank Sta=131.6,141.6
XS Rating Curve= 0 ,0
Exp/Cntr=0.3,0.1

Type RM Length L Ch R = 1 ,514     ,80,81.9,83.8
XS GIS Cut Line= 3
     1740471.337      169415.697     1740669.963      169374.919
     1740730.472      169260.479
#Sta/Elev= 28
     9.7 1107.93    19.3 1104.96    38.6 1099.17    48.3 1096.68    57.9 1094.81
    77.2 1091.76    86.9 1090.47    91.6 1090.26    96.6 1090.04   101.6 1090.64
   106.2  1091.2   125.5 1096.31   135.2 1098.29   154.5  1102.4   173.8 1106.88
   183.5 1109.61   193.1 1113.12   202.8 1117.51   212.7 1122.88   222.7 1128.83
   232.6 1135.05   252.6 1147.23   262.5 1152.74   272.5 1158.12   282.4 1163.28
   292.4 1168.35   322.3 1183.95   332.2 1188.72
#Mann= 3 , 0 , 0
       0      .1       0    91.6    .045       0   101.6      .1       0
Bank Sta=91.6,101.6
XS Rating Curve= 0 ,0
Exp/Cntr=0.3,0.1

Type RM Length L Ch R = 1 ,432.1   ,157.1,149.9,129.8
XS GIS Cut Line= 3
     1740441.083      169490.674     1740648.917      169468.313
     1740863.327      169093.423
#Sta/Elev= 30
      10 1109.85    59.7 1096.28    79.6 1091.58    89.6  1090.2   119.4 1087.31
   139.4 1084.91   144.3  1084.9   149.3 1084.88   154.3 1085.36     209 1091.43
   229.1 1095.58   249.2 1100.41   259.3  1103.4   269.3  1107.2   289.4 1116.27
   319.5 1130.94   359.7 1149.34   379.8  1158.9   399.9 1169.19   409.9 1174.65
   480.2 1213.89   490.3 1220.63   510.3 1236.89   520.4 1244.61   530.4 1251.29
   540.5 1257.11   550.5 1261.83   560.6  1265.6   610.8 1281.53   640.9 1289.86
#Mann= 3 , 0 , 0
       0      .1       0   144.3    .045       0   154.3      .1       0
Bank Sta=144.3,154.3
XS Rating Curve= 0 ,0
Exp/Cntr=0.3,0.1

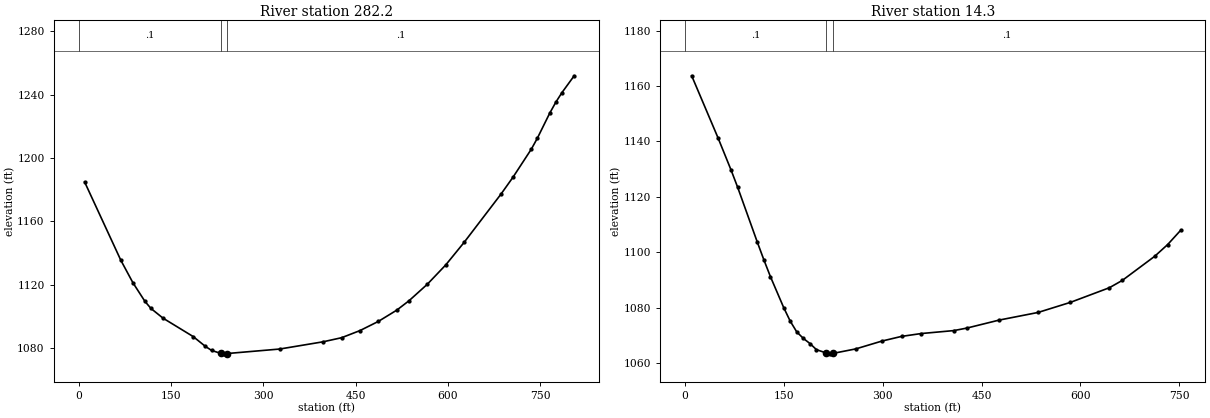
Type RM Length L Ch R = 1 ,282.2   ,274.4,267.9,274.3
XS GIS Cut Line= 4
     1740324.012      169516.983     1740485.807      169627.476
     1740697.587      169534.083     1740879.112      169202.601
#Sta/Elev= 30
     9.8 1184.85    68.6 1135.49    88.2 1121.34   107.8 1109.55   117.6 1105.09
   137.1    1099   186.1 1087.39     206 1081.18   216.1 1078.62   231.2 1076.75
   236.2 1076.48   241.2 1076.67   326.7 1079.51   397.2 1084.07   427.4 1086.66
   457.2 1091.15   487.1 1096.94   516.9 1104.02   536.8 1109.94   566.6 1120.36
   596.5 1132.53   626.3 1146.72     686 1177.05   705.9 1187.91   735.7 1205.62
   745.6 1212.61   765.5 1228.25   775.5 1235.23   785.4 1241.26   805.3 1251.89
#Mann= 3 , 0 , 0
       0      .1       0   231.2    .045       0   241.2      .1       0
Bank Sta=231.2,241.2
XS Rating Curve= 0 ,0
Exp/Cntr=0.3,0.1

Type RM Length L Ch R = 1 ,14.3    ,9.9,14.3,18.6
XS GIS Cut Line= 4
     1740317.435      169805.056     1740488.438      169907.657
     1740638.394      169762.963     1740789.665      169453.843
#Sta/Elev= 30
      10 1163.68    49.9 1141.32    69.8 1129.65    79.8 1123.42   109.7 1103.58
   119.7 1097.17   129.6 1091.14   149.6 1080.05   159.5 1075.16   169.5 1071.24
   179.5 1068.91   189.5 1067.06   199.4 1064.85   214.3 1063.65   219.3 1063.35
   224.3 1063.51     259 1065.13   298.7 1067.96   328.4 1069.64   358.2 1070.67
   407.8 1071.74   427.5 1072.64   476.6 1075.53   535.6 1078.28   584.8 1081.93
   643.8  1087.2   663.5 1089.85   712.6 1098.54   732.3 1102.78     752 1107.92
#Mann= 3 , 0 , 0
       0      .1       0   214.3    .045       0   224.3      .1       0
Bank Sta=214.3,224.3
XS Rating Curve= 0 ,0
Exp/Cntr=0.3,0.1

Chan Stop Cuts=-1
Use User Specified Reach Order=0